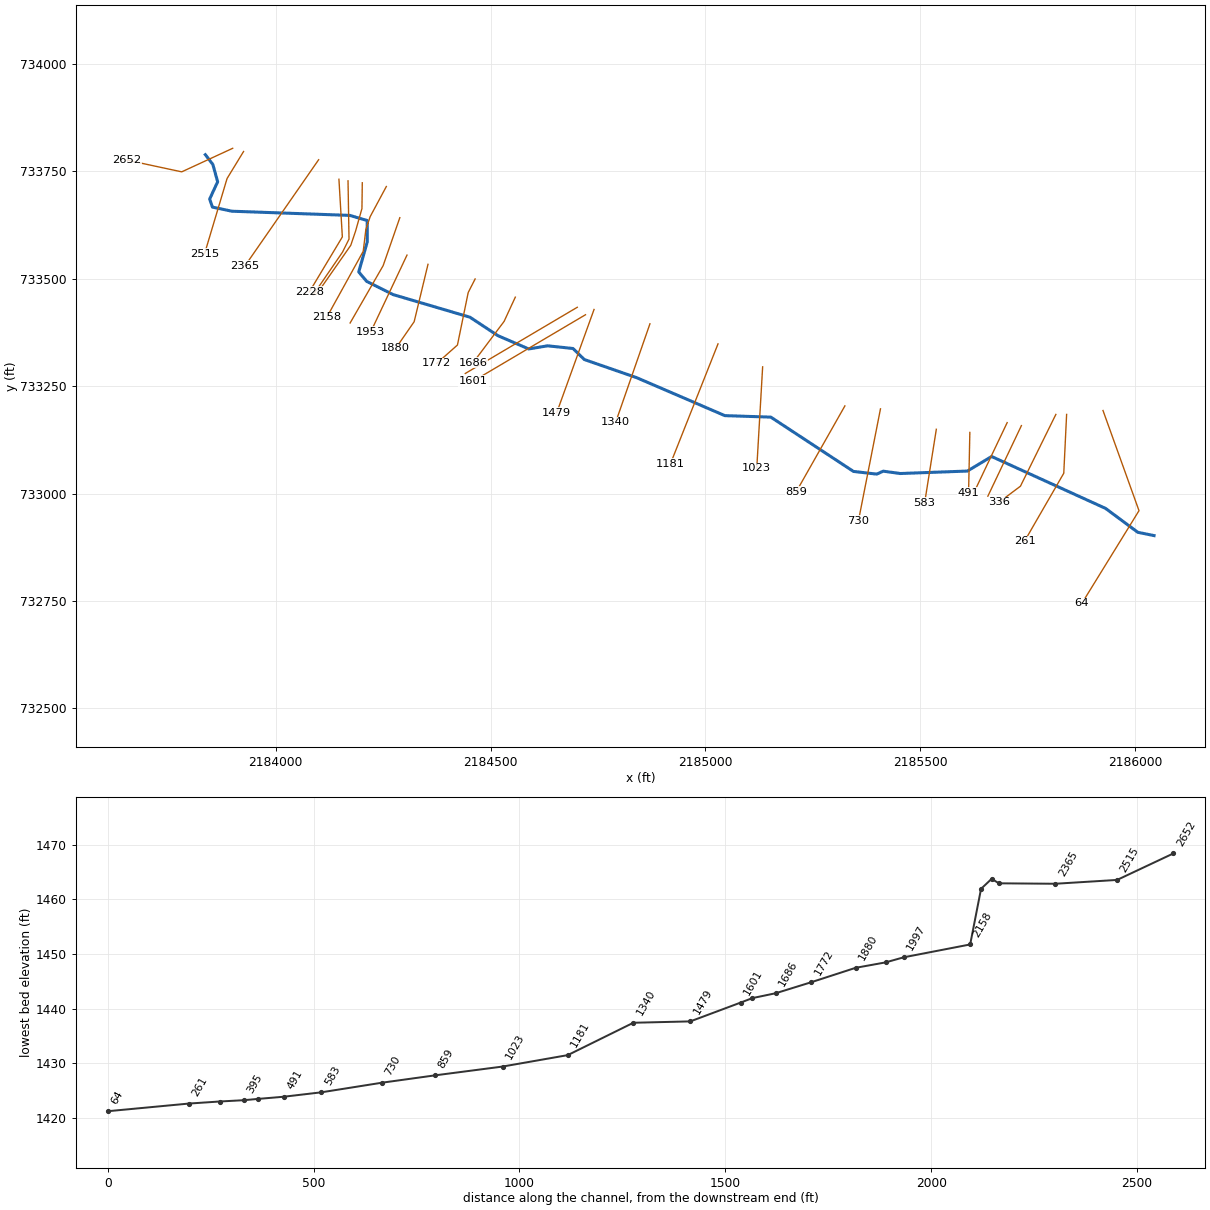
--- FINKRNT1A.prj (project) ---

Proj Title=FINKRNT1A
Current Plan=p01
Default Exp/Contr=0.3,0.1
English Units
Geom File=g01
Flow File=f01
Plan File=p01
Y Axis Title=Elevation
X Axis Title(PF)=Main Channel Distance
X Axis Title(XS)=Station
BEGIN DESCRIPTION:
---------- MODELED AS PART OF WVEMD CTP PROGRAM, 2023----------
Stream Name: Fink Run Tributary 1A
Flood Zone:  AFH
Upshur County, WV
HEC-RAS Version: RAS 6.3
Vertical Datum: NAVD88
Projection: NAD 1983 StatePlane West Virginia S FIPS 4702 (US Feet)
Terrain: 1-meter LIDAR (FEMA Region III 3DEP collected 2016-2018)
Land Use: 2019 NLCD
Hydrologic Method:
WV SIR2010-5033 regression equations
Additional Model Notes:
None
END DESCRIPTION:
DSS Export Rating Curves= 0
DSS Export Rating Curve Sorted= 0
DSS Export Volume Flow Curves= 0
DXF OffsetX= 0
DXF OffsetY= 0
DXF ScaleX= 1
DXF ScaleY= 10

--- FINKRNT1A.p01 (plan) ---

Plan Title=Floodplain
Program Version=4.10
Short Identifier=Floodplain
Geom File=g01
Flow File=f01
Subcritical Flow
K Sum by GR= 0
Std Step Tol= 0.01
Critical Tol= 0.01
Num of Std Step Trials= 20
Max Error Tol= 0.3
Flow Tol Ratio= 0.001
Split Flow NTrial= 30
Split Flow Tol= 0.02
Split Flow Ratio= 0.02
Log Output Level= 0
Friction Slope Method= 1
Unsteady Friction Slope Method= 2
Unsteady Bridges Friction Slope Method= 1
Parabolic Critical Depth
Global Vel Dist= 0 , 0 , 0
Global Log Level= 0
CheckData=True
Encroach Param=-1 ,0,0, 0
Computation Interval=1MIN
Output Interval=1HOUR
Run HTab= 0
Run UNet= 0
Run PostProcess= 0
Run WQNet= 0
UNET Theta= 1
UNET Theta Warmup= 1
UNET ZTol= 0.02
UNET ZSATol= 0.02
UNET MxIter= 20
UNET MaxInSteps= 0
UNET DtIC= 0
UNET DtMin= 0
UNET MaxCRTS= 20
UNET WFStab= 2
UNET SFStab= 1
UNET WFX= 1
UNET SFX= 1
UNET DSS MLevel= 4
UNET DZMax Abort= 100
UNET Convert EG Bridges= 0
UNET Use Existing IB Tables=-1
UNET Froude Reduction=False
UNET Froude Limit= 0.8
UNET Froude Power= 4
UNET Time Slicing=0,0, 5
UNET Junction Losses=0
Instantaneous Interval=1HOUR
Write IC File= 0
Write IC File at Sim End=0
Echo Input=False
Echo Parameters=False
Echo Output=False
Write Detailed= 0
WQ AD Non Conservative
WQ ULTIMATE=-1
WQ Max Comp Step=1HOUR
WQ Output Interval=15MIN
WQ Output Selected Increments= 0
WQ Output face flow=0
WQ Output face velocity=0
WQ Output face area=0
WQ Output face dispersion=0
WQ Output cell volume=0
WQ Output cell surface area=0
WQ Output cell continuity=0
WQ Output cumulative cell continuity=0
WQ Output face conc=0
WQ Output face dconc_dx=0
WQ Output face courant=0
WQ Output face peclet=0
WQ Output face adv mass=0
WQ Output face disp mass=0
WQ Output cell mass=0
WQ Output cell source sink temp=0
WQ Output cell source sink nsm=0
WQ Output MaxMinRange=-1
WQ Daily Max Min Mean=-1
WQ Daily Range=0
WQ Daily Time=0
WQ Create Restart=0
WQ Fixed Restart=0
WQ System Summary=0
WQ Use Fixed Temperature=0
Sorting and Armoring Iterations= 10
XS Update Threshold= 0.02
Hydraulics Update Threshold= 0.02
Energy Slope Method= 1
Volume Change Method= 1
XS Weighting Method= 0
Number of US Weighted Cross Sections= 1
Number of DS Weighted Cross Sections= 1
Upstream XS Weight=0
Main XS Weight=1
Downstream XS Weight=0
Number of DS XS's Weighted with US Boundary= 1
Upstream Boundary Weight= 1
Weight of XSs Associated with US Boundary= 0
Number of US XS's Weighted with DS Boundary= 1
Downstream Boundary Weight= 0.5
Weight of XSs Associated with DS Boundary= 0.5
Sediment Output Level= 3
Mass or Volume Output= 0
Output Increment Type= 1
Profile and TS Output Increment= 1
XS Output Flag= 0
XS Output Increment= 10
Disregard all LS=0
Disregard all Conn=0
Disregard all Breaches=0
Disregard all Pumps=0

--- FINKRNT1A.f01 (steady flow) ---

Flow Title=Flows
Program Version=4.10
Number of Profiles= 1
Profile Names=01pct
River Rch & RM=FINKRNT1A,Main            ,2652
    58.8
River Rch & RM=FINKRNT1A,Main            ,1479
    65.9
River Rch & RM=FINKRNT1A,Main            ,1181
    75.5
River Rch & RM=FINKRNT1A,Main            ,261
     136
Boundary for River Rch & Prof#=FINKRNT1A,Main            , 1
Up Type= 0
Dn Type= 3
Dn Slope=0.00731
DSS Import GetInterval= 0
DSS Import GetPeak= 0
DSS Import FillOption= 0

--- FINKRNT1A.g01 (geometry) ---

Geom Title=Geometry
Program Version=6.30

River Reach=FINKRNT1A       ,Main
Reach XY= 30
2183836.22902317733788.6879955832183853.58988084733766.118486926
2183864.87463517733725.7540663332183846.21161476733685.389317676
2183852.72210042733666.7262972592183897.86078967733657.177431837
2184172.55245401733647.4144163492184212.96514635733635.476031676
2184212.96514635733585.5630737542184193.19006925733515.868935316
2184211.72918034733493.8537408922184273.13998584733463.148338142
2184452.15827735733410.4277409692184517.04516617733367.556046564
2184588.84264448733336.5596103012184632.84357168733343.896234259
2184691.87134075733337.6462467612184718.26006751733311.951744333
2184840.23483263733269.6822437482185045.34340285733181.396231174
2185152.28807084733177.9241252542185344.64890659733051.535270423
2185398.81579301733045.2852829252185413.83975175733052.136037253
2185453.67690375733046.6740596742185609.74215735733052.403998743
2185666.17680684733086.2573138332185931.45449151732965.424222171
2186006.45466959732909.8685590032186044.26922651732902.175332919

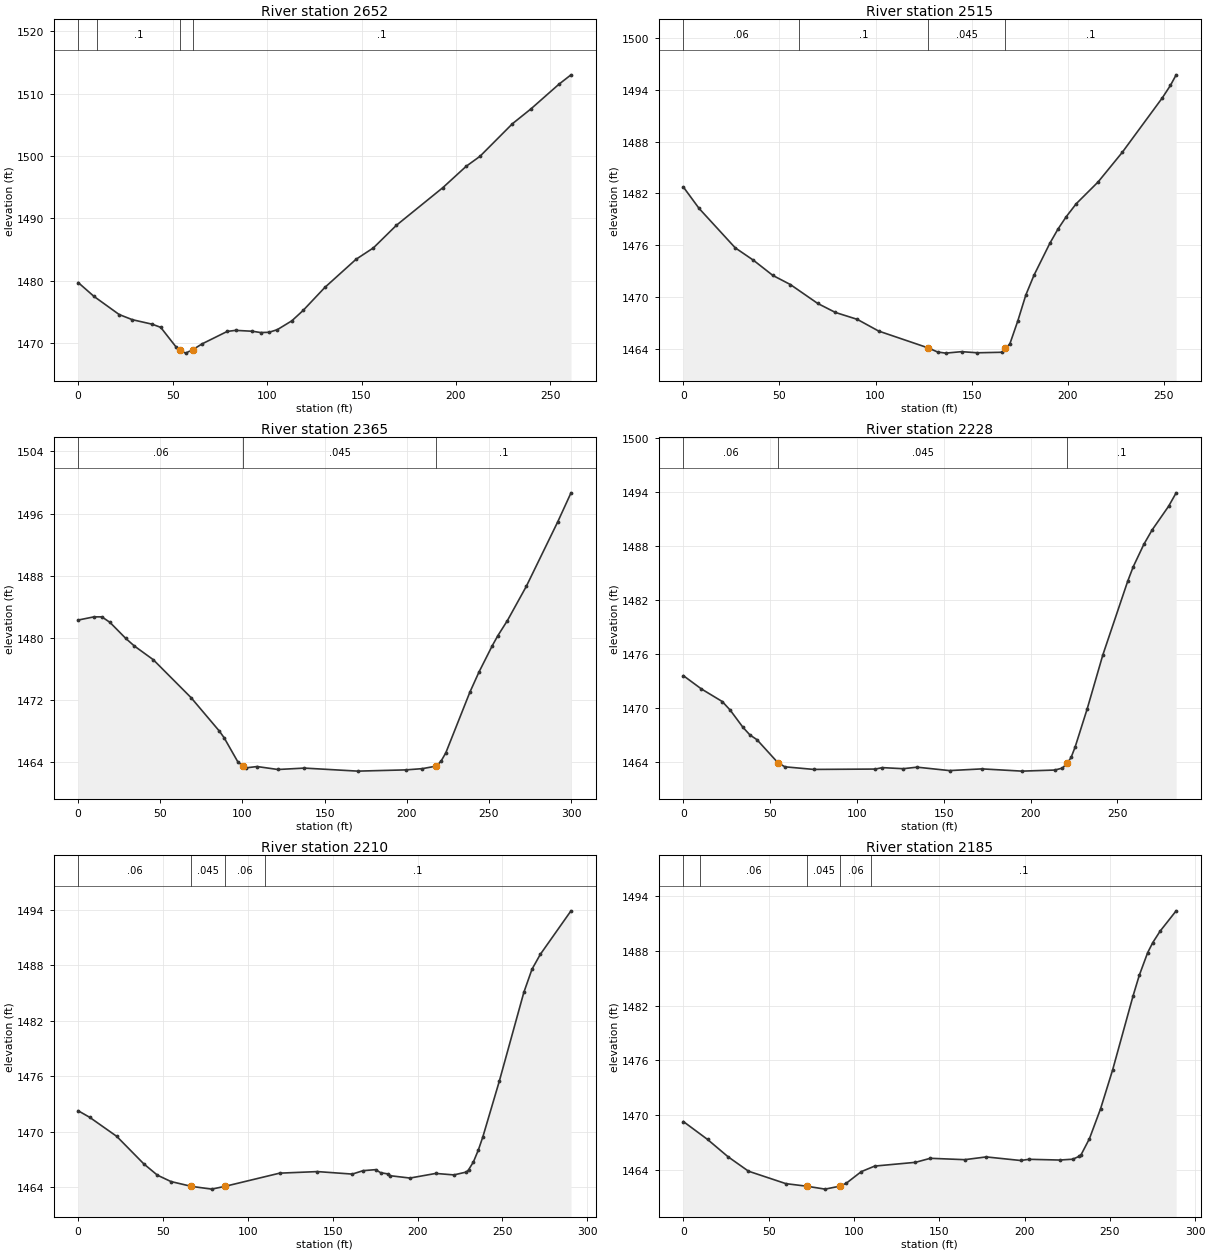
Type RM Length L Ch R = 1 ,2652    ,109.5,136.8,159.5
XS GIS Cut Line= 3
2183899.82918931733803.5741243252183781.24683748733748.780899686
2183653.90424889733776.076637658
#Sta/Elev= 30
       0 1479.73     8.4  1477.5    21.7  1474.6    28.7 1473.77    39.3 1473.04
    43.7 1472.54    51.7 1469.44    53.81468.868    56.9 1468.41    60.71468.976
    65.7 1469.91    78.9 1471.89    83.3 1472.06    92.2 1471.92    96.6 1471.71
     101 1471.75   105.4 1472.17   113.1 1473.59   119.1 1475.26   130.6 1478.95
   147.1 1483.46   156.3 1485.29   168.5 1488.92   193.1 1494.96   205.4 1498.37
   212.7 1499.97   229.9  1505.2   239.7 1507.58   254.5 1511.53   260.9 1513.04
#Mann= 4 ,-1,0
       0     .06       0      10      .1       0    53.8    .045       0
    60.7      .1       0
Bank Sta=53.8,60.7
XS Rating Curve= 0 ,0
Exp/Cntr(USF)=0,0
Exp/Cntr=0.3,0.1

Type RM Length L Ch R = 1 ,2515    ,172.4,150,124.4
XS GIS Cut Line= 3
2183925.18127832733796.2138404182183886.74424014 733733.24252255
2183834.40444347733558.231327434
#Sta/Elev= 30
       0 1482.75     8.2 1480.27      27 1475.72    36.4  1474.3    46.6 1472.53
    55.7 1471.48    69.9  1469.3    79.1 1468.26    90.5 1467.46   101.6 1466.11
   127.3 1464.17   132.3 1463.69   136.5 1463.56   144.8 1463.73     153  1463.6
   165.7 1463.66  167.581464.099   169.9 1464.64     174 1467.27   178.2 1470.28
   182.4 1472.54   190.7 1476.25   194.9 1477.88   199.1 1479.28   204.4 1480.81
   215.8 1483.33   228.3 1486.73   249.2 1493.04   253.4 1494.47   256.4  1495.7
#Mann= 4 ,-1,0
       0     .06       0      60      .1       0   127.3    .045       0
  167.58      .1       0
Bank Sta=127.3,167.58
XS Rating Curve= 0 ,0
Exp/Cntr(USF)=0,0
Exp/Cntr=0.3,0.1

Type RM Length L Ch R = 1 ,2365    ,109,137,155.3
XS GIS Cut Line= 2
2184099.91261457733777.0368522252183928.84598373733530.589681796
#Sta/Elev= 30
       0  1482.3     9.6 1482.71    14.4 1482.71    19.3 1482.01      29 1479.93
    34.2 1478.96    45.7  1477.2    68.7 1472.32    85.9 1468.02    88.8 1467.17
    97.2 1464.05   100.3 1463.52   102.1 1463.28   108.9 1463.45   121.6 1463.07
   137.7 1463.25   170.2 1462.86   199.5 1463.02   209.5 1463.18   218.1 1463.51
     221 1464.18   223.8 1465.22   238.4    1473     244 1475.62   252.1 1479.01
   255.5  1480.3   261.3 1482.24   272.8 1486.64     292 1494.97     300 1498.67
#Mann= 3 ,-1,0
       0     .06       0   100.3    .045       0   218.1      .1       0
Bank Sta=100.3,218.1
XS Rating Curve= 0 ,0
Exp/Cntr(USF)=0,0
Exp/Cntr=0.3,0.1

Type RM Length L Ch R = 1 ,2228    ,17.7,17.7,17.7
XS GIS Cut Line= 3
2184147.11676983733731.5511224722184155.06391964733597.332592223
2184078.24147141733469.295178498
#Sta/Elev= 30
       0 1473.57    10.4 1472.09    22.4 1470.69      27 1469.73    34.4  1467.8
    38.4 1466.96    42.4 1466.44    54.5 1463.87    58.5 1463.42    75.1 1463.13
   110.6 1463.17   114.6 1463.33   126.6 1463.21   134.6 1463.38   153.3    1463
     172 1463.19     195 1462.94   213.9 1463.06   218.3 1463.28   221.2 1463.86
   223.3 1464.46   225.6 1465.61   232.6 1469.89   241.6 1475.89   255.9 1484.08
   259.1  1485.7   265.2 1488.19   269.9 1489.77   279.5 1492.44   283.8 1493.92
#Mann= 3 ,-1,0
       0     .06       0    54.5    .045       0   221.2      .1       0
Bank Sta=54.5,221.2
XS Rating Curve= 0 ,0
Exp/Cntr(USF)=0,0
Exp/Cntr=0.3,0.1

Type RM Length L Ch R = 1 ,2210    ,52,25.7,52
XS GIS Cut Line= 4
2184168.27813872733727.9100184532184170.59552761733592.342768579
2184155.44029898733561.9255926892184087.12273528733462.266221573
#Sta/Elev= 30
       0 1472.25     6.7 1471.55    22.7 1469.48    38.7 1466.49    46.7 1465.27
    54.7 1464.58    66.7 1464.06    78.7 1463.76    86.7 1464.07   118.7 1465.49
     141 1465.66   161.5 1465.39   167.9 1465.76   175.3 1465.87   178.2 1465.54
   182.4 1465.41     184 1465.21   195.5 1464.96   210.7 1465.46   221.4  1465.3
   228.7 1465.61     230 1465.84   232.9 1466.71   235.8    1468   238.4 1469.39
   248.1 1475.42   262.6 1485.07   267.4 1487.58   272.3 1489.19   290.4 1493.91
#Mann= 4 ,-1,0
       0     .06       0    66.7    .045       0    86.7     .06       0
     110      .1       0
Bank Sta=66.7,86.7
XS Rating Curve= 0 ,0
Exp/Cntr(USF)=0,0
Exp/Cntr=0.3,0.1

Type RM Length L Ch R = 1 ,2185    ,25.3,26.4,24.7
XS GIS Cut Line= 5
2184201.48428673733723.3670948892184200.66516091733663.297868031
2184185.86628774733610.9557280822184174.70197277733577.859699003
2184094.81213583733463.488331361
#Sta/Elev= 30
       0 1469.32    14.2 1467.36    26.2 1465.47    38.2 1463.89    60.1 1462.53
    72.41462.247    83.1 1461.93   91.871462.258    95.5 1462.57   104.3 1463.84
   112.2 1464.45   136.1 1464.86   144.8  1465.3   164.9 1465.15   177.6 1465.45
   197.7 1465.06   202.7 1465.19   220.6 1465.11   228.3  1465.2   232.1 1465.52
   233.2  1465.7   238.1 1467.46   244.6 1470.72   251.6 1474.92   263.7 1483.09
   267.3 1485.31   272.2 1487.78   275.2 1488.88   279.5 1490.13   288.9 1492.35
#Mann= 5 ,-1,0
       0     .05       0      10     .06       0    72.4    .045       0
   91.87     .06       0  110.07      .1       0
Bank Sta=72.4,91.87
XS Rating Curve= 0 ,0
Exp/Cntr(USF)=0,0
Exp/Cntr=0.3,0.1

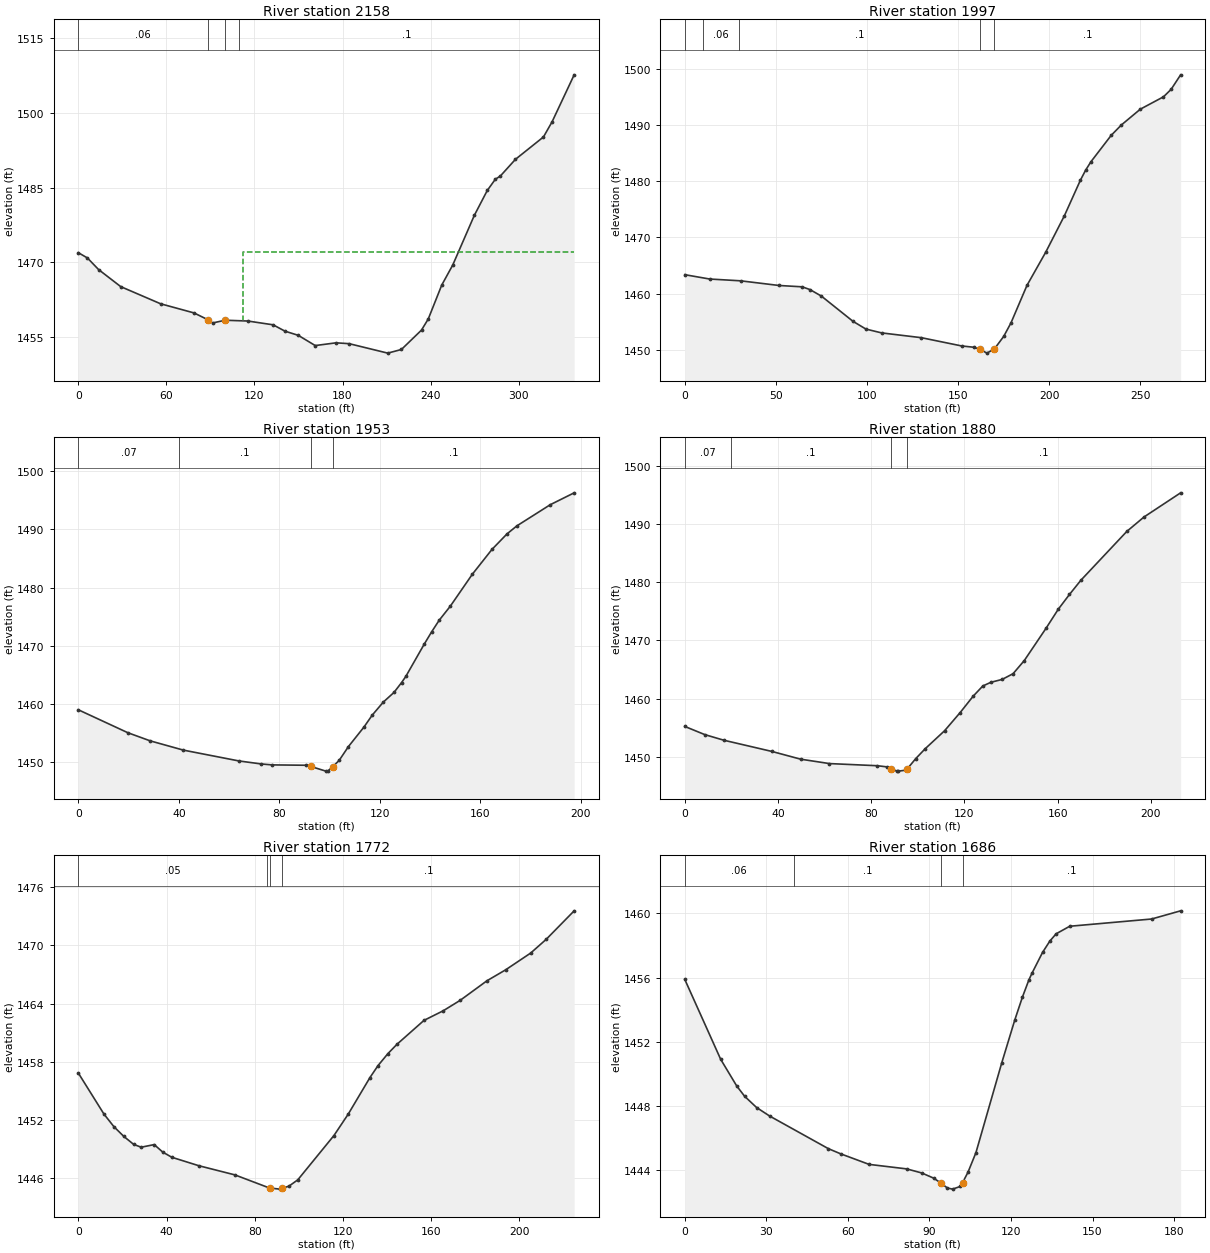
Type RM Length L Ch R = 1 ,2158    ,163.4,161.3,160.6
XS GIS Cut Line= 5
2184257.43808424733714.6354106082184219.85663656733644.599285431
2184209.81095172733614.9929251512184203.62983519733563.777959661
2184118.80970986733410.222445125
#Sta/Elev= 30
       0 1471.94     6.2 1470.88    13.8 1468.55    28.9 1465.12    56.1 1461.67
    78.8 1459.84    88.2 1458.48    91.5 1457.82     100 1458.37   115.5 1458.21
   132.7 1457.45   140.8 1456.17   149.8 1455.34   161.4 1453.28   175.6 1453.83
   184.5 1453.66   210.8 1451.76   220.1 1452.49   233.8 1456.39   238.4 1458.62
   247.6 1465.44   255.1 1469.47   269.8 1479.45   278.6 1484.44   284.1  1486.7
   287.5 1487.34   297.8  1490.7   316.9  1495.2   322.8 1498.26   337.8 1507.68
#Mann= 4 ,-1,0
       0     .06       0    88.2    .045       0     100     .06       0
  109.48      .1       0
#XS Ineff= 2 , 0
                             112         1472.03
Permanent Ineff=
       F       F
Bank Sta=88.2,100
XS Rating Curve= 0 ,0
Exp/Cntr(USF)=0,0
Exp/Cntr=0.3,0.1

Type RM Length L Ch R = 1 ,1997    ,43.6,44.1,44.4
XS GIS Cut Line= 3
2184288.80813832733642.0487693812184250.05624355733530.562549045
2184173.14863701 733397.01755784
#Sta/Elev= 30
       0 1463.37    13.6  1462.6    30.6 1462.28    51.7 1461.45    64.4 1461.21
    68.7 1460.72      75 1459.55    92.3 1455.07    99.4 1453.69     108 1453.01
   129.8 1452.16   151.9 1450.69   158.5 1450.46   162.2 1450.06   165.8 1449.41
   169.9 1450.16     175 1452.38     179 1454.79   187.8 1461.48   198.1 1467.39
   208.3 1473.85   217.1 1480.19     220 1481.99   222.9 1483.48     234 1488.17
   239.6 1490.02     250 1492.83   262.7 1495.03   266.9 1496.36   272.1 1498.94
#Mann= 5 ,-1,0
       0     .07       0      10     .06       0      30      .1       0
   162.2    .045       0   169.9      .1       0
Bank Sta=162.2,169.9
XS Rating Curve= 0 ,0
Exp/Cntr(USF)=0,0
Exp/Cntr=0.3,0.1

Type RM Length L Ch R = 1 ,1953    ,71.8,72.6,73.5
XS GIS Cut Line= 2
2184305.50126222  733555.00605192184221.29016812733376.578430629
#Sta/Elev= 30
       0 1459.02    19.7 1455.08    28.6 1453.68    41.8 1452.09    63.9 1450.23
    72.8 1449.71    77.2 1449.55    90.5 1449.49    92.5 1449.28    98.5 1448.48
    99.3 1448.49   101.31449.263   103.8 1450.33   107.5 1452.71   113.6 1456.02
     117 1458.13   121.4 1460.36   125.6    1462   128.6 1463.68   130.3 1464.74
   137.6 1470.27   140.6 1472.42   143.6 1474.41     148 1476.81   156.8 1482.32
   164.6 1486.58   170.6 1489.25   174.5 1490.62   187.8 1494.26   197.3  1496.3
#Mann= 4 ,-1,0
       0     .07       0      40      .1       0    92.5    .045       0
   101.3      .1       0
Bank Sta=92.5,101.3
XS Rating Curve= 0 ,0
Exp/Cntr(USF)=0,0
Exp/Cntr=0.3,0.1

Type RM Length L Ch R = 1 ,1880    ,108.7,108.9,108.8
XS GIS Cut Line= 3
2184354.38826793733533.5434640272184322.19438612733399.998472823
2184279.26921038733337.995441192
#Sta/Elev= 30
       0 1455.19     8.6 1453.78    16.8 1452.81    37.4 1450.88    49.7 1449.55
    62.1 1448.79    82.7 1448.42    86.8 1448.22    88.3 1447.93    90.9 1447.51
    91.7 1447.49      95 1447.66   95.551447.918    99.1 1449.64   103.2 1451.36
   111.5 1454.45   118.2 1457.59   123.8 1460.42   127.9 1462.16   131.4  1462.8
   136.2 1463.29   140.9 1464.28   145.7 1466.54     155 1472.08   160.3 1475.39
   165.1 1477.93     170 1480.38   189.7 1488.79   197.1 1491.28   212.8 1495.44
#Mann= 4 ,-1,0
       0     .07       0      20      .1       0    88.3    .045       0
   95.55      .1       0
Bank Sta=88.3,95.55
XS Rating Curve= 0 ,0
Exp/Cntr(USF)=0,0
Exp/Cntr=0.3,0.1

Type RM Length L Ch R = 1 ,1772    ,86.8,85.3,84.1
XS GIS Cut Line= 4
2184464.14283654733499.5191555592184447.98899837733467.963334418
2184422.94931252733345.7458201462184374.65848981733302.820644401
#Sta/Elev= 30
       0 1456.82    11.6 1452.59    16.1 1451.29    20.6 1450.28    25.1 1449.45
    28.5 1449.16    34.4 1449.43    38.3 1448.65    42.4 1448.12    54.6 1447.25
      71  1446.3    86.71444.943    91.4 1444.83    92.51444.915    95.5 1445.14
    99.5 1445.79   115.9 1450.37   122.4 1452.59   132.2 1456.35   135.9  1457.6
   140.4 1458.84   144.5  1459.8   156.7 1462.26   165.4 1463.25   173.1 1464.33
   185.3 1466.36   193.7 1467.48   205.1 1469.22   212.1 1470.63   224.8 1473.58
#Mann= 4 ,-1,0
       0     .05       0   85.45      .1       0    86.7    .045       0
    92.5      .1       0
Bank Sta=86.7,92.5
XS Rating Curve= 0 ,0
Exp/Cntr(USF)=0,0
Exp/Cntr=0.3,0.1

Type RM Length L Ch R = 1 ,1686    ,59.6,56.6,55.7
XS GIS Cut Line= 3
2184557.62812724733457.1391571122184531.45461788733400.594655819
2184459.31647531733304.609193391
#Sta/Elev= 30
       0 1455.89    13.2 1450.92    19.1 1449.26      22 1448.62    26.4 1447.92
    31.2 1447.39    52.8 1445.36    57.3 1445.04    67.8 1444.38    81.6  1444.1
    87.1 1443.85    91.6 1443.52    94.31443.207    96.6 1442.91    98.5 1442.84
   101.4 1443.01  102.191443.243   104.2  1443.9   107.1 1445.11   116.6  1450.7
   121.4 1453.37   124.2 1454.79   126.6 1455.87   127.7 1456.27   131.6 1457.57
   134.3 1458.28   136.6 1458.73   141.6  1459.2   171.7 1459.65   182.4 1460.16
#Mann= 4 ,-1,0
       0     .06       0      40      .1       0    94.3    .045       0
  102.19      .1       0
Bank Sta=94.3,102.19
XS Rating Curve= 0 ,0
Exp/Cntr(USF)=0,0
Exp/Cntr=0.3,0.1

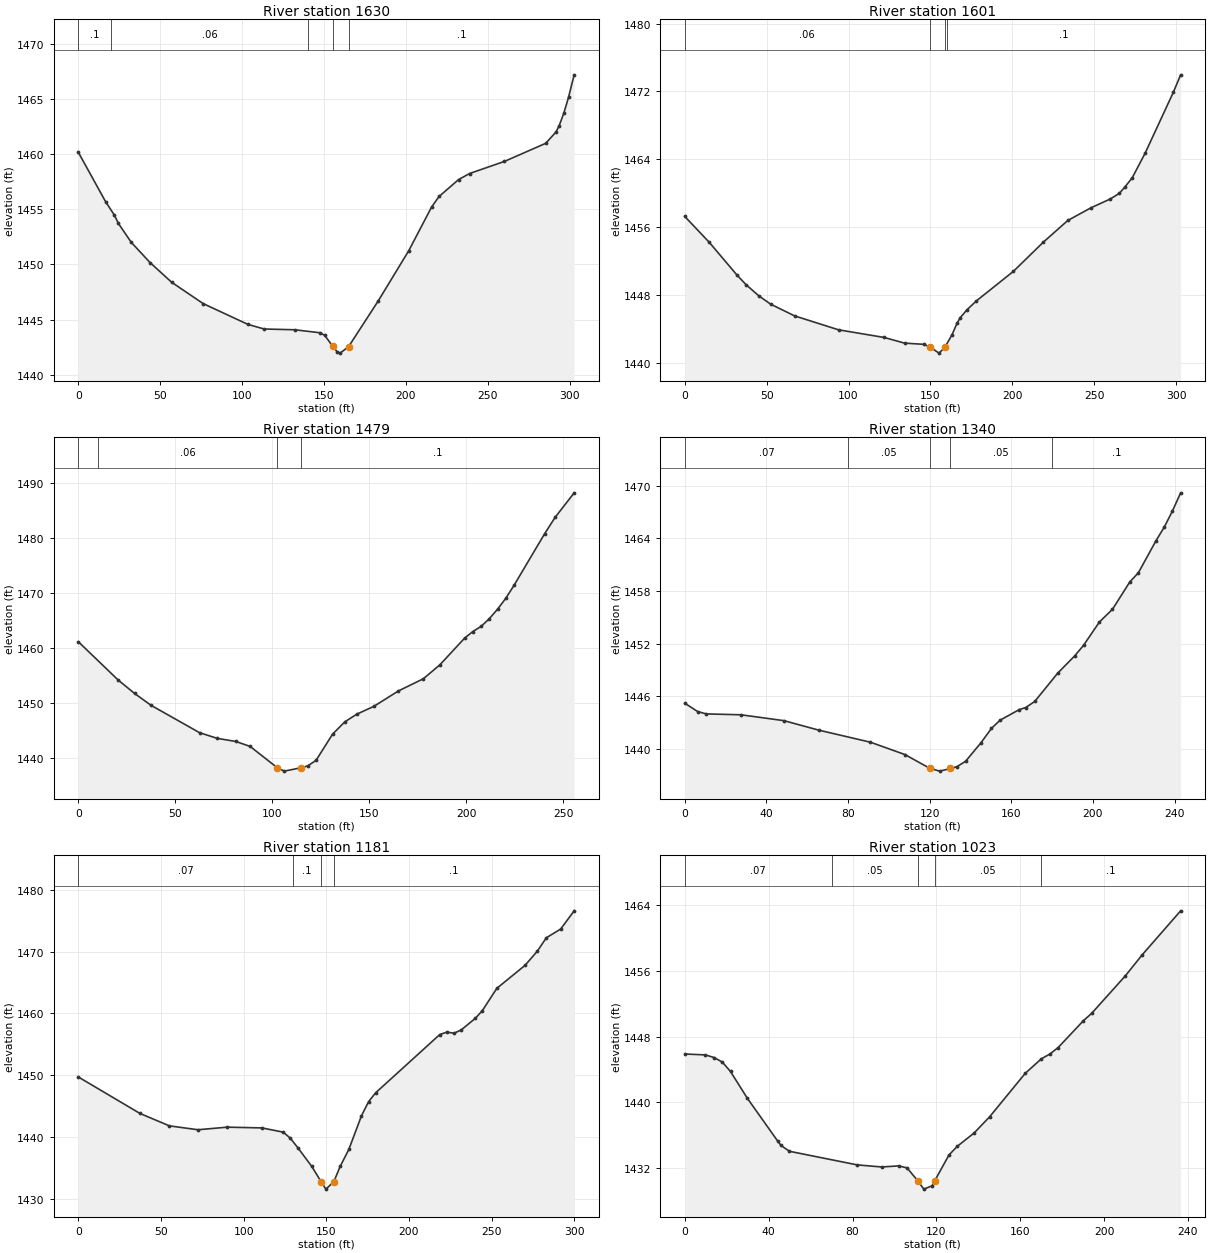
Type RM Length L Ch R = 1 ,1630    ,28.1,28.6,28.4
XS GIS Cut Line= 2
2184701.85692989733433.6016298362184441.15068013733279.495268867
#Sta/Elev= 30
       0 1460.18    16.6 1455.71      22 1454.48    24.4 1453.74    32.3 1452.01
    43.8 1450.17      57 1448.38    76.3 1446.44   103.7 1444.55   113.5 1444.14
   132.1 1444.07   147.6  1443.8   150.5 1443.56   155.3 1442.58     158 1442.08
   159.9 1441.95   165.1 1442.55   183.2  1446.7   201.8 1451.25   215.7  1455.2
   220.3 1456.17   232.2  1457.7   238.9 1458.25   260.2 1459.35   285.4 1460.99
   291.7 1462.02   293.6 1462.58   296.5 1463.73   299.4 1465.19   302.8 1467.21
#Mann= 5 ,-1,0
       0      .1       0      20     .06       0     140      .1       0
   155.3    .045       0   165.1      .1       0
Bank Sta=155.3,165.1
XS Rating Curve= 0 ,0
Exp/Cntr(USF)=0,0
Exp/Cntr=0.3,0.1

Type RM Length L Ch R = 1 ,1601    ,118.2,122.2,122.5
XS GIS Cut Line= 2
2184720.97538821733416.2212131852184460.26913845733262.114852216
#Sta/Elev= 30
       0 1457.25    14.9 1454.21      32 1450.31    37.4 1449.21    45.3 1447.87
    52.5  1446.9    67.1 1445.52    93.9 1443.88   121.7 1442.98   134.2 1442.31
   145.9 1442.17   149.6 1441.86   155.3 1441.13   158.9 1441.84   163.2  1443.3
   166.3 1444.67   168.2  1445.3   172.2 1446.22     178 1447.28   200.7 1450.78
   218.9 1454.21   233.9 1456.78   248.1 1458.28   259.8 1459.31   265.4 1459.98
   268.6 1460.69   273.2  1461.8   281.1 1464.71   298.3 1471.88   302.8 1473.96
#Mann= 4 ,-1,0
       0     .06       0   149.6    .045       0   158.9     .06       0
     160      .1       0
Bank Sta=149.6,158.9
XS Rating Curve= 0 ,0
Exp/Cntr(USF)=0,0
Exp/Cntr=0.3,0.1

Type RM Length L Ch R = 1 ,1479    ,137.9,138.3,137.9
XS GIS Cut Line= 2
2184740.85929699733428.4703346332184653.93499901733188.012183883
#Sta/Elev= 30
       0 1461.21    20.5 1454.26      29 1451.81    37.5 1449.65    62.5 1444.68
    71.6 1443.65    81.2 1443.08    88.6 1442.18   102.6 1438.31   106.2 1437.69
   114.91438.304   118.3 1438.64   122.6 1439.65   131.1  1444.4   137.4 1446.64
   143.7 1448.06   152.4 1449.46   165.1 1452.27   177.9 1454.47   186.4 1456.99
   199.2 1461.86   203.4 1463.05   207.7 1463.99   211.9 1465.38   216.2 1467.12
   220.4 1469.08   224.7 1471.46   240.5 1480.85   245.9 1483.82   255.7 1488.27
#Mann= 4 ,-1,0
       0      .1       0      10     .06       0   102.6    .045       0
   114.9      .1       0
Bank Sta=102.6,114.9
XS Rating Curve= 0 ,0
Exp/Cntr(USF)=0,0
Exp/Cntr=0.3,0.1

Type RM Length L Ch R = 1 ,1340    ,160.1,159.4,159.5
XS GIS Cut Line= 2
2184870.95916241733395.1251470672184791.07064088733165.594693433
#Sta/Elev= 30
       0 1445.19     6.3 1444.24    10.5 1443.97    27.5 1443.87    48.6  1443.2
    65.6 1442.12      91 1440.74   107.9 1439.33     120 1437.77   124.9 1437.44
   130.2 1437.74   133.4 1437.95   137.6 1438.56   145.1 1440.66   150.3 1442.32
   154.5 1443.25   163.9 1444.46   167.1  1444.7   171.5 1445.39   182.8 1448.63
     191 1450.57   195.4 1451.79   203.2 1454.46   209.6 1455.91   218.1 1459.03
   222.3 1460.08   230.8 1463.68     235  1465.3     239 1467.13     243  1469.2
#Mann= 5 ,-1,0
       0     .07       0      80     .05       0     120    .045       0
   130.2     .05       0     180      .1       0
Bank Sta=120,130.2
XS Rating Curve= 0 ,0
Exp/Cntr(USF)=0,0
Exp/Cntr=0.3,0.1

Type RM Length L Ch R = 1 ,1181    ,157,158.2,159.5
XS GIS Cut Line= 2
2185029.39025678733348.4370576762184918.79248269733069.567675409
#Sta/Elev= 30
       0 1449.69    37.3 1443.78    55.1 1441.77    72.4 1441.14    90.1 1441.56
   111.1 1441.44     124 1440.75   128.3 1439.76   132.9 1438.19   141.2 1435.22
   146.91432.723   149.8 1431.52   154.61432.729   158.4 1435.19   163.7 1437.97
   171.3 1443.39   175.6 1445.68   179.9 1447.13   218.7 1456.57     223 1456.96
   227.3 1456.78   231.6  1457.3   240.2 1459.19   244.5 1460.46   253.2 1464.05
   270.3 1467.78   277.7 1470.07   283.2 1472.25   291.8 1473.65     300 1476.61
#Mann= 4 ,-1,0
       0     .07       0     130      .1       0   146.9    .045       0
   154.6      .1       0
Bank Sta=146.9,154.6
XS Rating Curve= 0 ,0
Exp/Cntr(USF)=0,0
Exp/Cntr=0.3,0.1

Type RM Length L Ch R = 1 ,1023    ,165.7,164.2,162.2
XS GIS Cut Line= 2
2185133.27968085733294.9664036632185119.56747193733058.877937069
#Sta/Elev= 30
       0 1445.89     9.8 1445.78    14.1 1445.45    17.9  1444.9    21.8 1443.76
    29.8 1440.51    44.4 1435.25    45.9 1434.75    49.9 1434.04    82.3 1432.38
    93.9 1432.13     102 1432.26     106 1432.02   111.3 1430.39     114 1429.43
     118 1429.84  119.171430.422     126 1433.59     130 1434.65     138 1436.27
   145.4 1438.24   162.4 1443.54   170.1 1445.31   174.1 1445.88   178.1 1446.68
   190.1 1449.94   194.1 1450.85   210.1  1455.4   218.2 1457.98   236.5 1463.33
#Mann= 5 ,-1,0
       0     .07       0      70     .05       0   111.3    .045       0
  119.17     .05       0     170      .1       0
Bank Sta=111.3,119.17
XS Rating Curve= 0 ,0
Exp/Cntr(USF)=0,0
Exp/Cntr=0.3,0.1

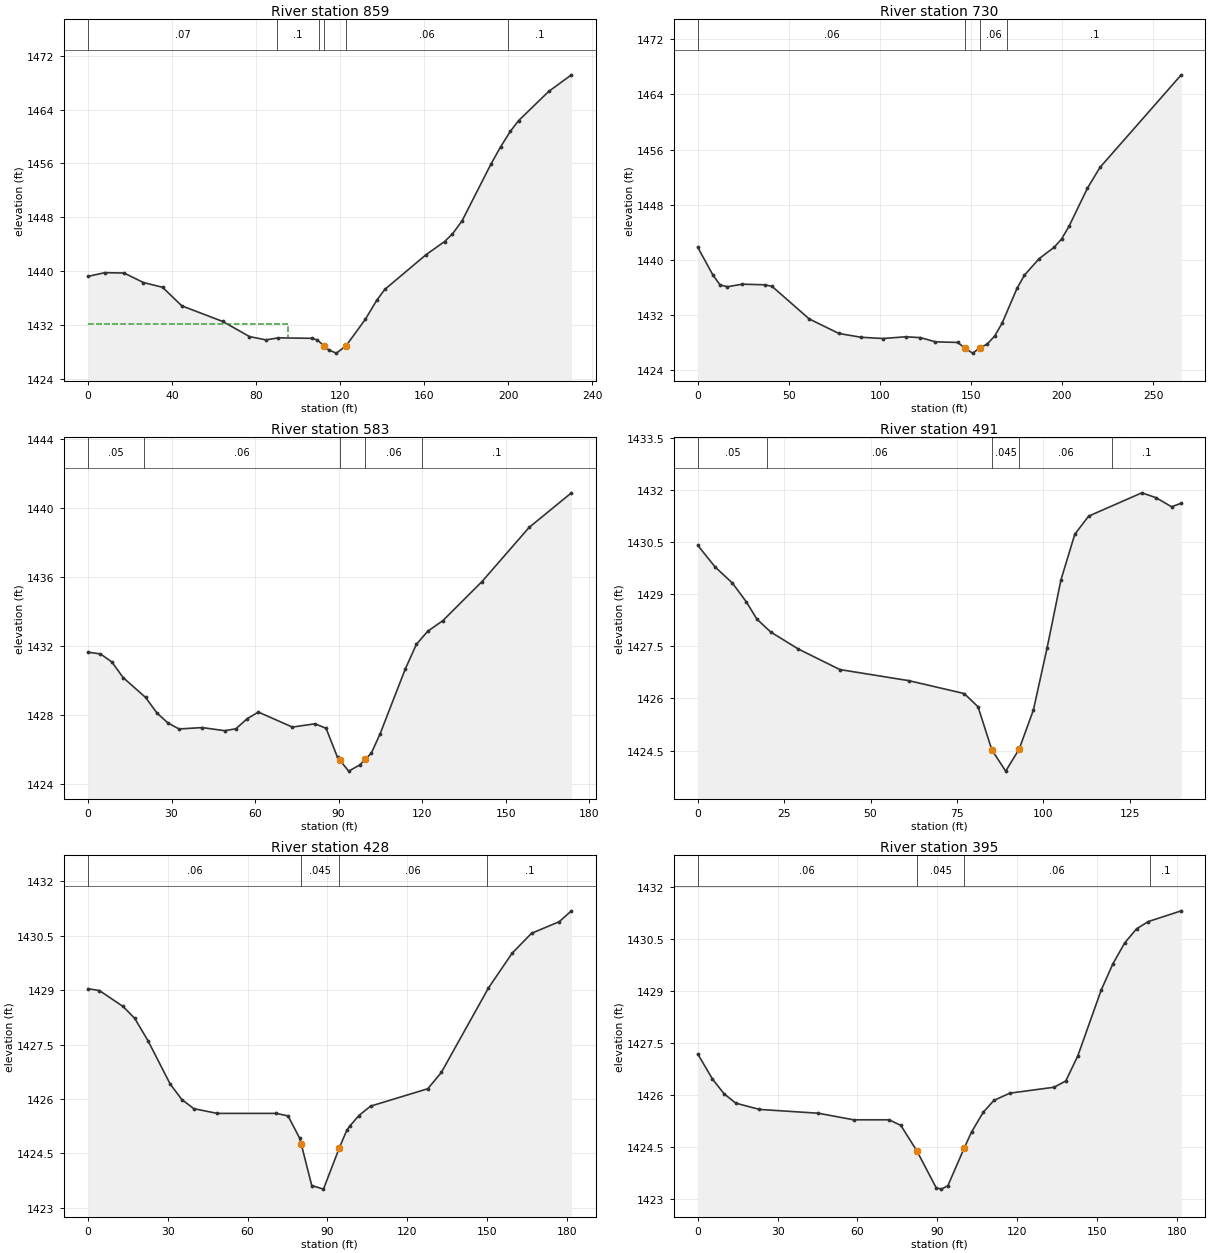
Type RM Length L Ch R = 1 ,859     ,127.3,128.5,129.8
XS GIS Cut Line= 2
2185324.72725065733204.1066975332185211.24651282 733003.83919145
#Sta/Elev= 30
       0 1439.22       8 1439.77    17.2 1439.72    26.4 1438.31    35.5  1437.6
    44.7 1434.84    64.2 1432.52    76.9 1430.28    84.7 1429.79    90.7 1430.09
   106.6 1430.02   109.1 1429.79   112.4  1428.9   114.7 1428.27   118.3 1427.82
   122.9  1428.9   122.9 1428.91   132.1 1432.86   137.5 1435.67   141.3 1437.28
     161 1442.45   169.8  1444.4   173.5 1445.51   178.1 1447.46   191.9 1455.92
   196.5 1458.48   201.1 1460.76     205 1462.35   219.4  1466.7   230.2 1469.16
#Mann= 6 ,-1,0
       0     .07       0      90      .1       0     110     .06       0
   112.4    .045       0   122.9     .06       0     200      .1       0
#XS Ineff= 2 , 0
            95.4 1432.18
Permanent Ineff=
       F       F
Bank Sta=112.4,122.9
XS Rating Curve= 0 ,0
Exp/Cntr(USF)=0,0
Exp/Cntr=0.3,0.1

Type RM Length L Ch R = 1 ,730     ,147.4,147.4,147.5
XS GIS Cut Line= 2
2185407.52385921733197.1923922452185356.25212152732936.660422796
#Sta/Elev= 30
       0 1441.83     8.2 1437.86    12.2 1436.37    16.3 1436.11    24.5 1436.48
    36.7 1436.39    40.8 1436.16    61.2 1431.44    77.5 1429.33    89.7 1428.78
   101.6  1428.6   114.2 1428.85   122.3 1428.73   130.5 1428.12   142.7 1428.03
   146.8  1427.2   150.9 1426.48   154.9 1427.22     159 1427.81   163.1 1428.98
   167.2 1430.86   175.3 1435.87   179.4 1437.79   187.5 1440.19   195.7 1441.83
   199.8 1443.04   203.9 1444.89     214 1450.41   220.9 1453.42   265.5 1466.84
#Mann= 4 ,-1,0
       0     .06       0   146.8    .045       0   154.9     .06       0
     170      .1       0
Bank Sta=146.8,154.9
XS Rating Curve= 0 ,0
Exp/Cntr(USF)=0,0
Exp/Cntr=0.3,0.1

Type RM Length L Ch R = 1 ,583     ,90.6,91.5,91.8
XS GIS Cut Line= 2
2185537.49911272733149.6449582082185510.26606227732978.150343179
#Sta/Elev= 30
       0 1431.63     4.5 1431.53     8.6 1431.06    12.6 1430.16    20.7    1429
    24.8 1428.09    28.8 1427.51    32.7 1427.17      41 1427.25    49.1 1427.07
    53.1 1427.18    57.2 1427.77    61.2 1428.15    73.4 1427.28    81.5 1427.47
    85.5 1427.21    89.6 1425.52    90.51425.346    93.6 1424.72    97.7 1425.09
    99.4  1425.4   101.7 1425.75   104.9 1426.89   113.9 1430.64   117.9 1432.08
     122 1432.85   127.4 1433.46   141.4 1435.72   158.4 1438.88   173.6 1440.89
#Mann= 5 ,-1,0
       0     .05       0      20     .06       0    90.5    .045       0
    99.4     .06       0     120      .1       0
Bank Sta=90.5,99.4
XS Rating Curve= 0 ,0
Exp/Cntr(USF)=0,0
Exp/Cntr=0.3,0.1

Type RM Length L Ch R = 1 ,491     ,67.1,62.9,58.8
XS GIS Cut Line= 2
2185615.51812214733142.2846743012185612.57400857733002.439280072
#Sta/Elev= 23
       0  1430.4     5.1 1429.77      10 1429.32    14.1 1428.77    17.1 1428.28
    21.1 1427.91    29.1 1427.42    41.1 1426.83    61.1 1426.51    77.1 1426.14
    81.1 1425.76    85.1 1424.52    89.1 1423.91      931424.544    97.1 1425.66
   101.1 1427.46   105.1 1429.41   109.1 1430.72   113.1 1431.24   128.5 1431.91
   132.6 1431.77   137.1 1431.51   139.9 1431.61
#Mann= 5 ,-1,0
       0     .05       0      20     .06       0    85.1    .045       0
      93     .06       0     120      .1       0
Bank Sta=85.1,93
XS Rating Curve= 0 ,0
Exp/Cntr(USF)=0,0
Exp/Cntr=0.3,0.1

Type RM Length L Ch R = 1 ,428     ,33.4,33.4,33.2
XS GIS Cut Line= 2
2185702.36947224733165.1015544122185624.35046282 733000.96722329
#Sta/Elev= 27
       0 1429.04     4.3 1428.99    13.2 1428.55    17.6 1428.22    22.6  1427.6
    30.9 1426.41    35.3 1425.98    39.8 1425.73    48.6  1425.6    70.8  1425.6
    75.2 1425.53    79.6 1424.91    80.11424.766    84.1 1423.61    88.5 1423.51
    94.51424.656    97.3 1425.14    98.3 1425.24   101.8 1425.54   106.2  1425.8
   127.7 1426.28   132.8 1426.73   150.5 1429.06   159.4 1430.02   166.7 1430.57
   177.1 1430.89   181.7 1431.19
#Mann= 4 ,-1,0
       0     .06       0    80.1    .045       0    94.5     .06       0
     150      .1       0
Bank Sta=80.1,94.5
XS Rating Curve= 0 ,0
Exp/Cntr(USF)=0,0
Exp/Cntr=0.3,0.1

Type RM Length L Ch R = 1 ,395     ,59.4,59.4,59.2
XS GIS Cut Line= 2
2185735.49074982  733158.1092847 2185657.4717404732993.974953579
#Sta/Elev= 27
       0 1427.18     5.5 1426.46     9.9 1426.03    14.3 1425.76    23.2 1425.58
    45.3 1425.47    58.6 1425.28    71.9 1425.28    76.3 1425.12    82.3 1424.39
    89.6 1423.32    91.6 1423.28      94 1423.38   100.21424.476   102.9 1424.93
   107.3  1425.5   111.3 1425.84   117.3 1426.05   133.9 1426.22   138.3  1426.4
   142.8 1427.12   151.6 1429.02     156 1429.78   160.5 1430.39   164.9 1430.79
   169.3    1431   181.7 1431.31
#Mann= 4 ,-1,0
       0     .06       0    82.3    .045       0   100.2     .06       0
     170      .1       0
Bank Sta=82.3,100.2
XS Rating Curve= 0 ,0
Exp/Cntr(USF)=0,0
Exp/Cntr=0.3,0.1

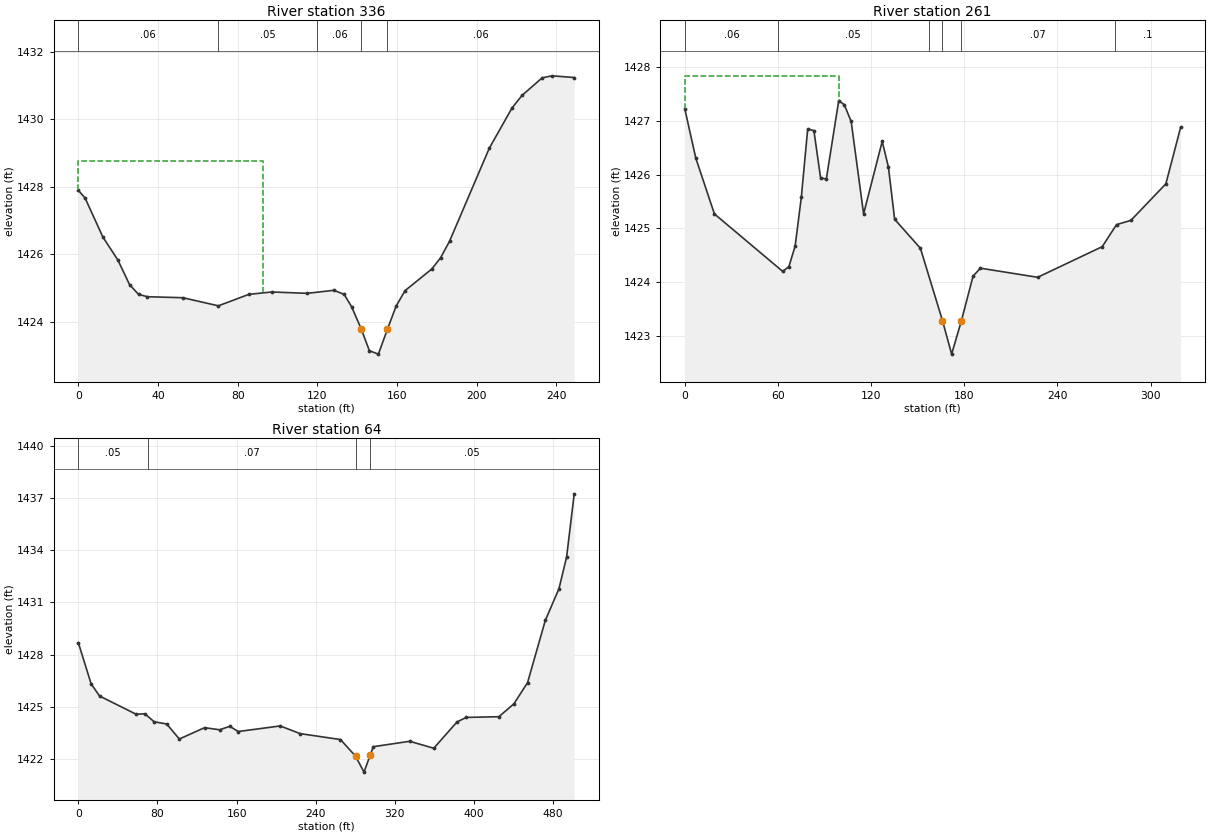
Type RM Length L Ch R = 1 ,336     ,75.3,74.9,74.5
XS GIS Cut Line= 3
 2185815.7178444 733184.238292572185733.28266464733017.159847885
2185683.23273408 732979.62239996
#Sta/Elev= 30
       0 1427.89     3.4 1427.66    12.3 1426.51    19.9 1425.82    25.7  1425.1
    30.2 1424.81    34.6 1424.74    52.5 1424.71    70.3 1424.47    85.6 1424.81
    97.1 1424.88   114.9 1424.84   128.3 1424.93   133.4 1424.81   137.2 1424.44
     1421423.783   146.1 1423.14   150.6 1423.04   155.1 1423.77   159.5 1424.46
     164 1424.92   177.4 1425.56   181.8 1425.89   186.3 1426.38   206.3 1429.14
   217.7 1430.33   222.7  1430.7   232.8 1431.22   237.7 1431.28   248.9 1431.23
#Mann= 5 ,-1,0
       0     .06       0      70     .05       0     120     .06       0
     142    .045       0   155.1     .06       0
#XS Ineff= 2 , 0
           92.74 1428.76
Permanent Ineff=
       F       F
Bank Sta=142,155.1
XS Rating Curve= 0 ,0
Exp/Cntr(USF)=0,0
Exp/Cntr=0.3,0.1

Type RM Length L Ch R = 1 ,261     ,196.4,196.8,195.7
XS GIS Cut Line= 3
2185840.74280968 733184.238292572185834.11855417733047.337011903
2185742.94817227732889.442479253
#Sta/Elev= 30
       0 1427.23     7.1 1426.31    19.1 1425.27    63.1  1424.2    67.1 1424.29
    71.1 1424.67    75.1 1425.58    79.2 1426.85    83.2 1426.82    87.5 1425.94
    91.2 1425.92    99.2 1427.38   102.8  1427.3   107.2 1426.99   115.2 1425.27
   127.2 1426.62   131.2 1426.14   135.2 1425.17   151.8 1424.63     1661423.285
   171.9 1422.66   178.1 1423.27   185.7 1424.11   190.4 1424.26   227.3 1424.09
   268.9 1424.66   278.1 1425.07   287.4 1425.15   309.9 1425.83   319.4 1426.88
#Mann= 6 ,-1,0
       0     .06       0      60     .05       0  157.06     .07       0
     166    .045       0   178.1     .07       0  277.06      .1       0
#XS Ineff= 2 , 0
           99.18 1427.84
Permanent Ineff=
       F       F
Bank Sta=166,178.1
XS Rating Curve= 0 ,0
Exp/Cntr(USF)=0,0
Exp/Cntr=0.3,0.1

Type RM Length L Ch R = 1 ,64      ,,,
XS GIS Cut Line= 3
2185925.43361614733193.2958398632186009.21710544732960.158204543
2185876.12573808 732744.37327979
#Sta/Elev= 30
       0 1428.69    12.9 1426.33    21.4 1425.63    58.5 1424.58    67.2 1424.61
    76.6 1424.15    89.4 1424.02   102.1 1423.16   127.6 1423.81   142.9 1423.69
   153.1 1423.89   161.6 1423.59   204.1 1423.91   224.2 1423.47     265 1423.13
 280.2181422.178   288.8 1421.26295.0177 1422.23   298.2 1422.72     335 1423.03
   359.3 1422.63   382.8 1424.14   392.2  1424.4   425.1 1424.44   440.2 1425.17
   454.1 1426.39   472.1 1429.97   485.9 1431.79   493.6  1433.6   501.3 1437.23
#Mann= 4 ,-1,0
       0     .05       0      70     .07       0 280.218    .045       0
295.0177     .05       0
Bank Sta=280.218,295.0177
XS Rating Curve= 0 ,0
Exp/Cntr(USF)=0,0
Exp/Cntr=0.3,0.1
LCMann Table=0

Chan Stop Cuts=-1
Use User Specified Reach Order=0
Composite Channel Slope=5